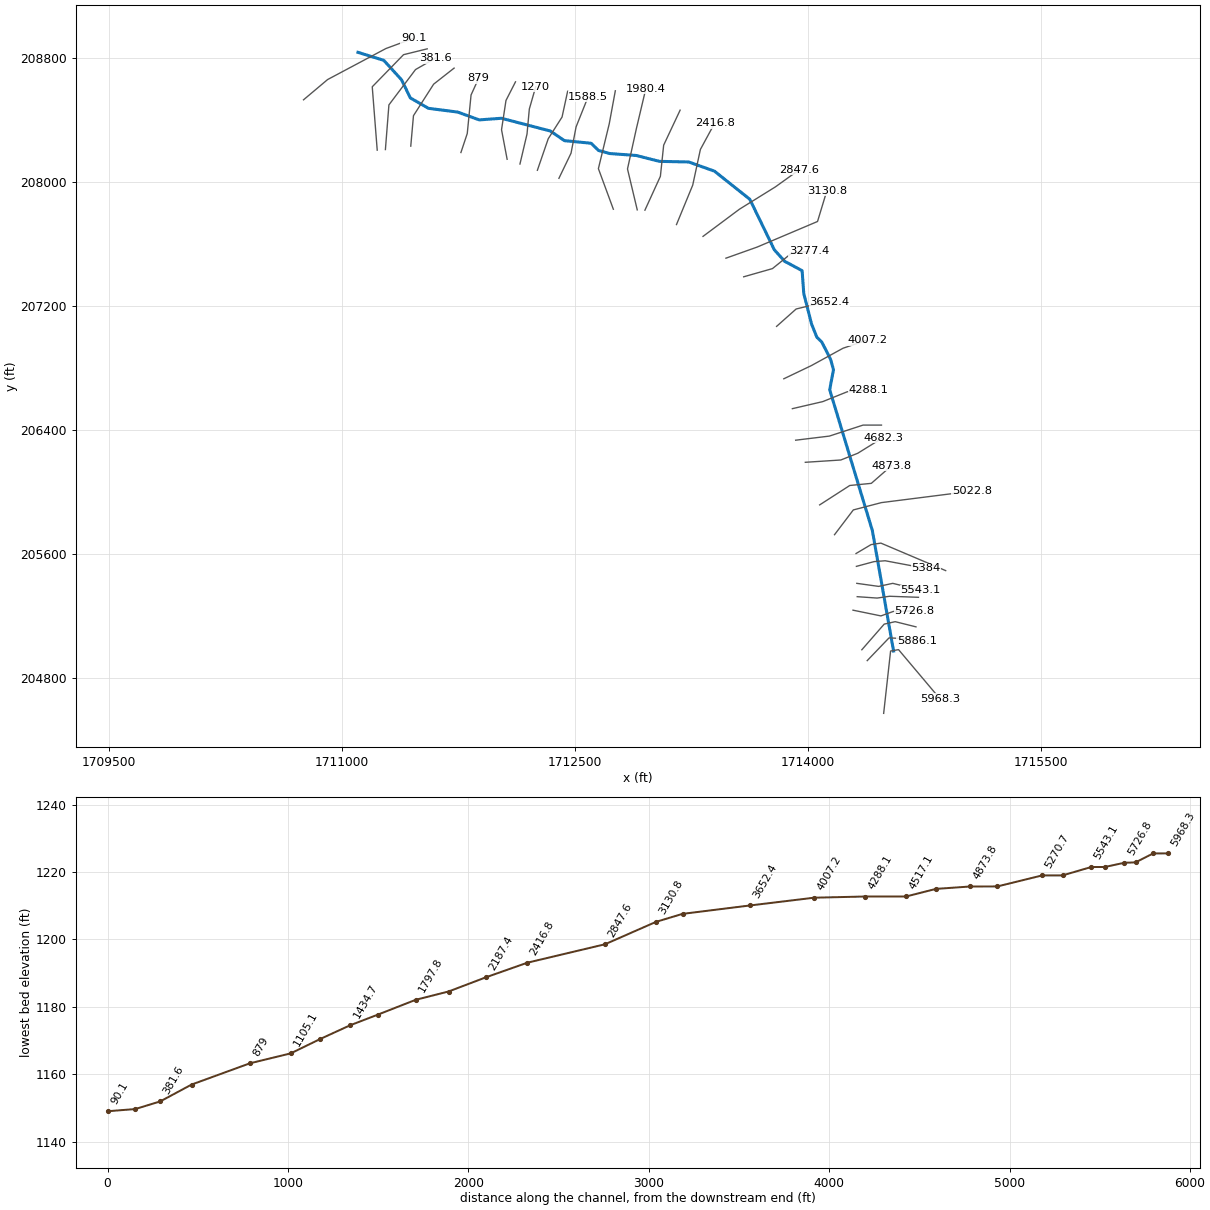
--- lftfrkglbr.prj (project) ---

Proj Title=lftfrkglbr
Current Plan=p01
Default Exp/Contr=0,0
English Units
Geom File=g01
Flow File=f01
Plan File=p01
BEGIN DESCRIPTION:
END DESCRIPTION:
DSS Export Rating Curves= 0
DSS Export Rating Curve Sorted= 0
DSS Export Volume Flow Curves= 0
DXF OffsetX= 0
DXF OffsetY= 0
DXF ScaleX= 0
DXF ScaleY= 0

--- lftfrkglbr.p01 (plan) ---

Plan Title=Floodplain
Program Version=4.00
Geom File=g01
Flow File=f01
K Sum by GR=0
Std Step Tol=0.01
Critical Tol=0.01
Num of Std Step Trials=20
Max Error Tol=0.3
Flow Tol Ratio=0.001
Split Flow NTrial=30
Split Flow Tol=0.02
Split Flow Ratio=0.02
Log Output Level=0
Friction Slope Method=1
Unsteady Friction Slope Method=2
Unsteady Bridges Friction Slope Method=1
Global Log Level=0
CheckData=False
Run HTab=0
Run UNet=0
Run PostProcess=0
UNET Theta=0
UNET Theta Warmup=0
UNET ZTol=0
UNET ZSATol=0
UNET MxIter=0
UNET MaxInSteps=0
UNET DtIC=0
UNET DtMin=0
UNET MaxCRTS=0
UNET WFStab=0
UNET SFStab=0
UNET WFX=0
UNET SFX=0
UNET DSS MLevel=0
UNET DZMax Abort=0
UNET Convert EG Bridges=0
UNET Use Existing IB Tables=0
UNET Froude Limit=0
UNET Froude Power=0
Write IC File=0
Echo Input=False
Echo Output=False
Write Detailed=0

--- lftfrkglbr.f01 (steady flow) ---

Flow Title=NFF Regression Equation
Program Version=4.00
Number of Profiles= 1
Profile Names=P100yr
River Rch & RM=lftfrkglbr,Main            ,5968.3
     320
River Rch & RM=lftfrkglbr,Main            ,5618.2
     389
River Rch & RM=lftfrkglbr,Main            ,5384
     389
River Rch & RM=lftfrkglbr,Main            ,5022.8
     501
River Rch & RM=lftfrkglbr,Main            ,3277.4
     526
River Rch & RM=lftfrkglbr,Main            ,3277.4
     681
River Rch & RM=lftfrkglbr,Main            ,242.8
     738
Boundary for River Rch & Prof#=lftfrkglbr,Main            , 1
Up Type= 0
Dn Type= 1
Dn Known WS=1149.3
DSS Import GetInterval= 0
DSS Import GetPeak= 0
DSS Import FillOption= 0

--- lftfrkglbr.g01 (geometry) ---

Geom Title=USGS 10m DEM
Program Version=4.00

River Reach=lftfrkglbr      ,Main
Reach XY= 30
     1714549.924      204973.986     1714413.502      205750.404
     1714138.697      206658.599     1714163.148      206787.843
     1714144.443      206854.864     1714087.629       206966.87
     1714056.184      206997.018     1714021.581      207083.602
     1713971.737      207279.783     1713961.125      207426.512
     1713848.723      207486.974     1713782.223      207561.041
     1713624.442      207886.626     1713397.285      208067.944
      1713231.33       208127.33     1713043.225      208131.316
     1712893.246      208169.125     1712721.989      208181.865
     1712650.505      208201.409     1712602.262      208248.079
      1712430.85      208264.851     1712339.607      208327.071
     1712025.236      208409.185     1711882.135      208398.709
     1711743.844      208449.049     1711554.963      208473.258
     1711438.215      208540.609     1711382.282      208656.702
      1711267.36       208782.76      1711100.95      208834.349

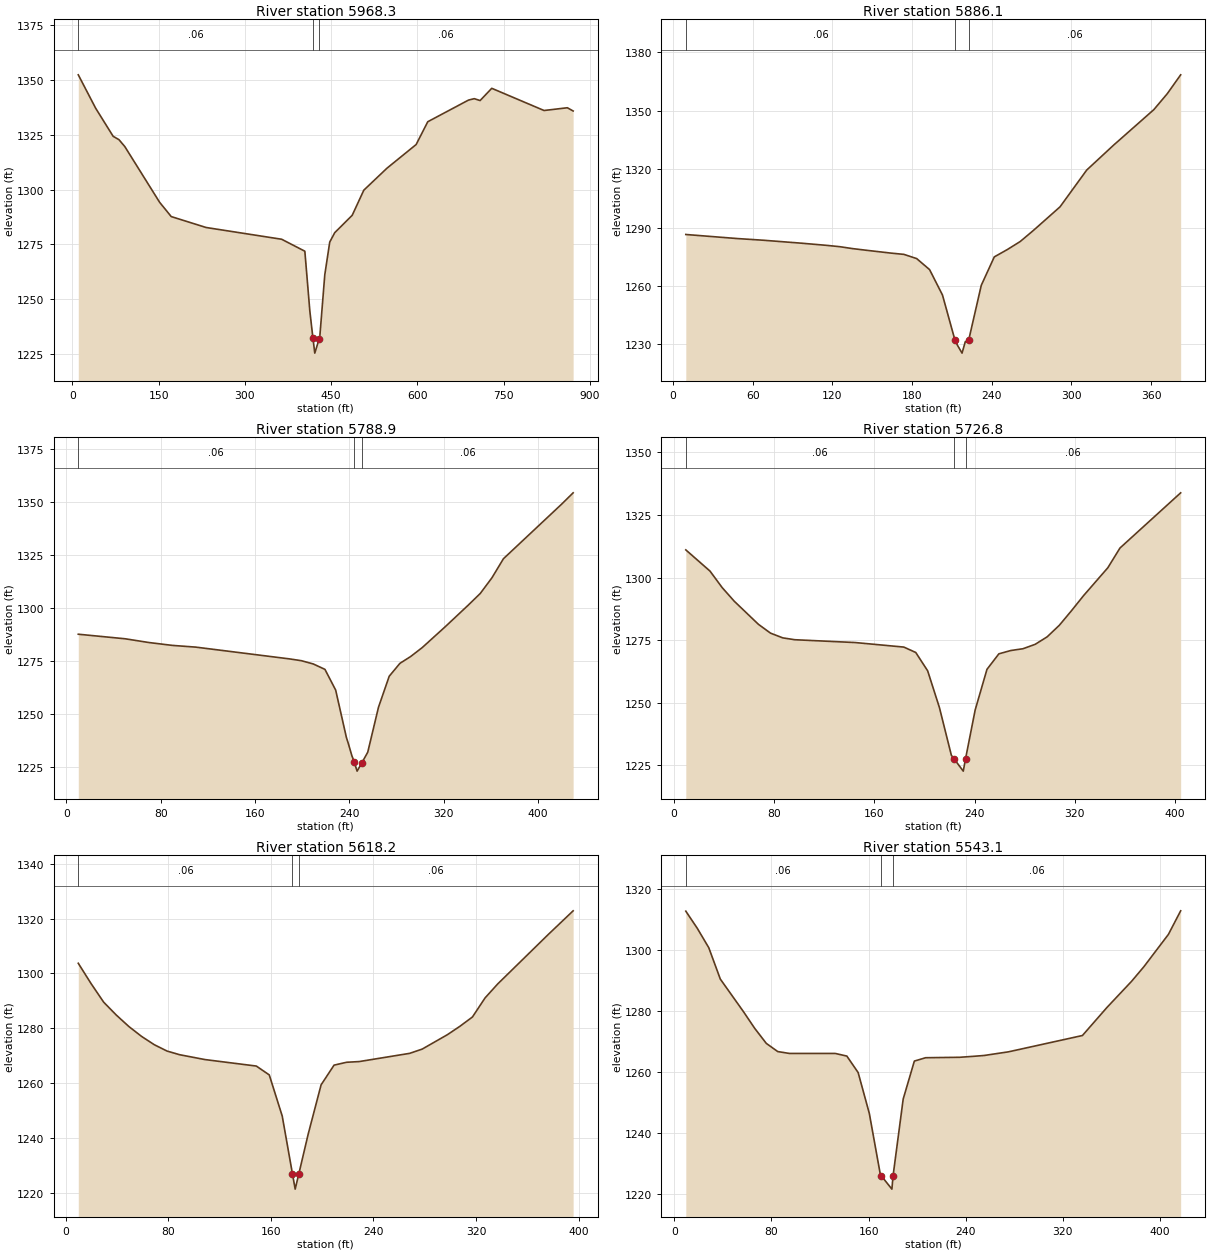
Type RM Length L Ch R = 1 ,5968.3  ,84.4,82.2,77.7
XS GIS Cut Line= 4
     1714486.203      204572.065     1714530.781      204973.906
     1714581.964      204983.075     1714849.114      204665.771
#Sta/Elev= 30
    10.1 1352.26    40.4 1337.02    70.8 1324.25    80.9 1322.72      91  1319.6
   151.6 1294.21   171.8  1287.7   232.5 1282.72   363.9 1277.37   404.3 1271.92
     413 1244.62  418.41 1232.25   421.6  1225.5   429.1 1231.89   430.3 1232.91
     439 1261.19   447.6 1276.08   456.3 1280.36   486.7 1288.28   506.9 1299.72
   547.4 1309.78   597.9  1320.5   618.2  1330.9     689 1340.75   699.1  1341.4
   709.2 1340.54   729.5 1346.12   820.5 1336.01     861 1337.26   871.1 1335.79
#Mann= 3 , 0 , 0
    10.1     .06       0  418.41    .045       0   429.1     .06       0
Bank Sta=418.41,429.1
XS Rating Curve= 0 ,0
Exp/Cntr=0.3,0.1

Type RM Length L Ch R = 1 ,5886.1  ,98.1,97.2,102.6
XS GIS Cut Line= 4
     1714380.321       204912.21     1714520.646      205058.707
     1714588.877      205055.647     1714699.027      205041.386
#Sta/Elev= 30
     9.7 1286.46    48.3 1284.38    67.6 1283.53    96.6    1282   115.9 1280.86
   125.6 1280.19   135.2 1279.21   144.9 1278.41   164.2 1276.89   173.9 1276.24
   183.5 1274.07   193.2 1268.41   202.9 1255.36  212.38 1231.98   212.6 1231.38
  217.64 1225.49   220.1 1231.43   222.4 1231.44  222.57 1231.98   232.1 1260.33
   241.9 1274.94   251.6 1278.67   261.4 1282.84   271.2 1288.46   291.4 1300.68
   311.5  1319.6   331.7 1332.37     362 1350.63   372.1 1358.81   382.2 1368.52
#Mann= 3 , 0 , 0
     9.7     .06       0  212.38    .045       0  222.57     .06       0
Bank Sta=212.38,222.57
XS Rating Curve= 0 ,0
Exp/Cntr=0.3,0.1

Type RM Length L Ch R = 1 ,5788.9  ,59.4,62.1,64.7
XS GIS Cut Line= 4
     1714345.645      204982.224     1714489.644      205147.528
       1714560.5      205163.358     1714694.263       205129.93
#Sta/Elev= 30
      10 1287.57    49.8 1285.41    69.8 1283.65    89.7 1282.29   109.6 1281.47
   189.3 1275.89   199.3 1275.04   209.3 1273.51   219.2 1270.95   228.3 1261.16
   237.4 1238.74     239 1235.95  242.01 1230.17  242.86 1228.97  244.08 1226.98
   246.5 1222.84  250.55 1226.82   255.5 1231.78   264.6 1253.02   273.7 1267.69
   282.8  1273.8   291.8 1276.99   301.7 1281.24   321.4  1291.2   341.1 1301.51
   350.9 1306.82   360.8 1314.22   370.6 1323.27   419.9 1349.04   429.7 1354.42
#Mann= 3 , 0 , 0
      10     .06       0  244.08    .045       0  250.55     .06       0
Bank Sta=244.08,250.55
XS Rating Curve= 0 ,0
Exp/Cntr=0.3,0.1

Type RM Length L Ch R = 1 ,5726.8  ,112.8,108.7,104.5
XS GIS Cut Line= 4
       1714288.7        205237.5     1714468.528      205200.486
     1714548.772      205229.424     1714684.204      205233.033
#Sta/Elev= 30
     9.7 1311.08      29 1302.61    38.7 1296.02    48.3  1290.6    67.6 1281.36
    77.3 1277.82      87 1275.95    96.6  1275.2   144.9 1274.07   183.6 1272.26
   193.1 1270.11   202.6 1262.78     212 1248.08   221.5 1229.07   223.5 1227.73
     231 1222.72  232.79 1227.59   240.5 1247.16   249.9 1263.36   259.4 1269.57
   268.9 1270.89   278.6  1271.6   288.3 1273.35   297.9 1276.35   307.6 1280.96
   317.3 1286.78     327 1292.84   346.3 1303.94     356 1311.83   404.4 1333.87
#Mann= 3 , 0 , 0
     9.7     .06       0   223.5    .045       0  232.79     .06       0
Bank Sta=223.5,232.79
XS Rating Curve= 0 ,0
Exp/Cntr=0.3,0.1

Type RM Length L Ch R = 1 ,5618.2  ,73.7,75.1,76.5
XS GIS Cut Line= 4
     1714315.903      205324.504     1714444.103      205315.571
     1714524.061      205327.184     1714710.331      205320.484
#Sta/Elev= 30
     9.9 1303.72    19.8 1296.37    29.7 1289.55    39.5 1284.88    49.4 1280.66
    59.3 1277.07    69.2 1274.05    79.1 1271.75      89 1270.41   108.7 1268.65
   148.7 1266.29   158.8 1263.06   168.9 1248.08  176.83 1227.15     179 1221.47
  181.86 1227.06   189.1 1241.43   199.2 1259.44   209.3 1266.62   219.1 1267.67
   228.9 1267.92   268.2 1270.91     278 1272.46   297.6 1277.69   307.4 1280.76
   317.2 1284.16     327 1291.08   336.8 1296.15   376.1 1314.11   395.7 1322.82
#Mann= 3 , 0 , 0
     9.9     .06       0  176.83    .045       0  181.86     .06       0
Bank Sta=176.83,181.86
XS Rating Curve= 0 ,0
Exp/Cntr=0.3,0.1

Type RM Length L Ch R = 1 ,5543.1  ,161.8,159,156.3
XS GIS Cut Line= 4
     1714313.334      205410.477     1714454.042      205390.823
      1714544.72      205410.477      1714721.61      205366.925
#Sta/Elev= 30
     9.5 1312.59    18.9    1307    28.4 1300.62    37.9 1290.33    56.8 1279.74
    66.3 1274.14    75.8 1269.23    85.2 1266.56    94.7 1265.95   132.6 1265.94
   142.1 1265.08   151.4 1259.69   160.6  1246.3   169.9 1225.79   171.7 1225.21
   179.2 1221.46  180.13  1225.7   188.5 1250.99   197.7 1263.44     207 1264.54
   234.9 1264.68     245 1264.96   255.1 1265.27   275.3 1266.48   336.1 1271.82
   356.3 1281.02   376.5 1289.56   386.7 1294.37   406.9 1304.97     417  1312.7
#Mann= 3 , 0 , 0
     9.5     .06       0   169.9    .045       0  180.13     .06       0
Bank Sta=169.9,180.13
XS Rating Curve= 0 ,0
Exp/Cntr=0.3,0.1

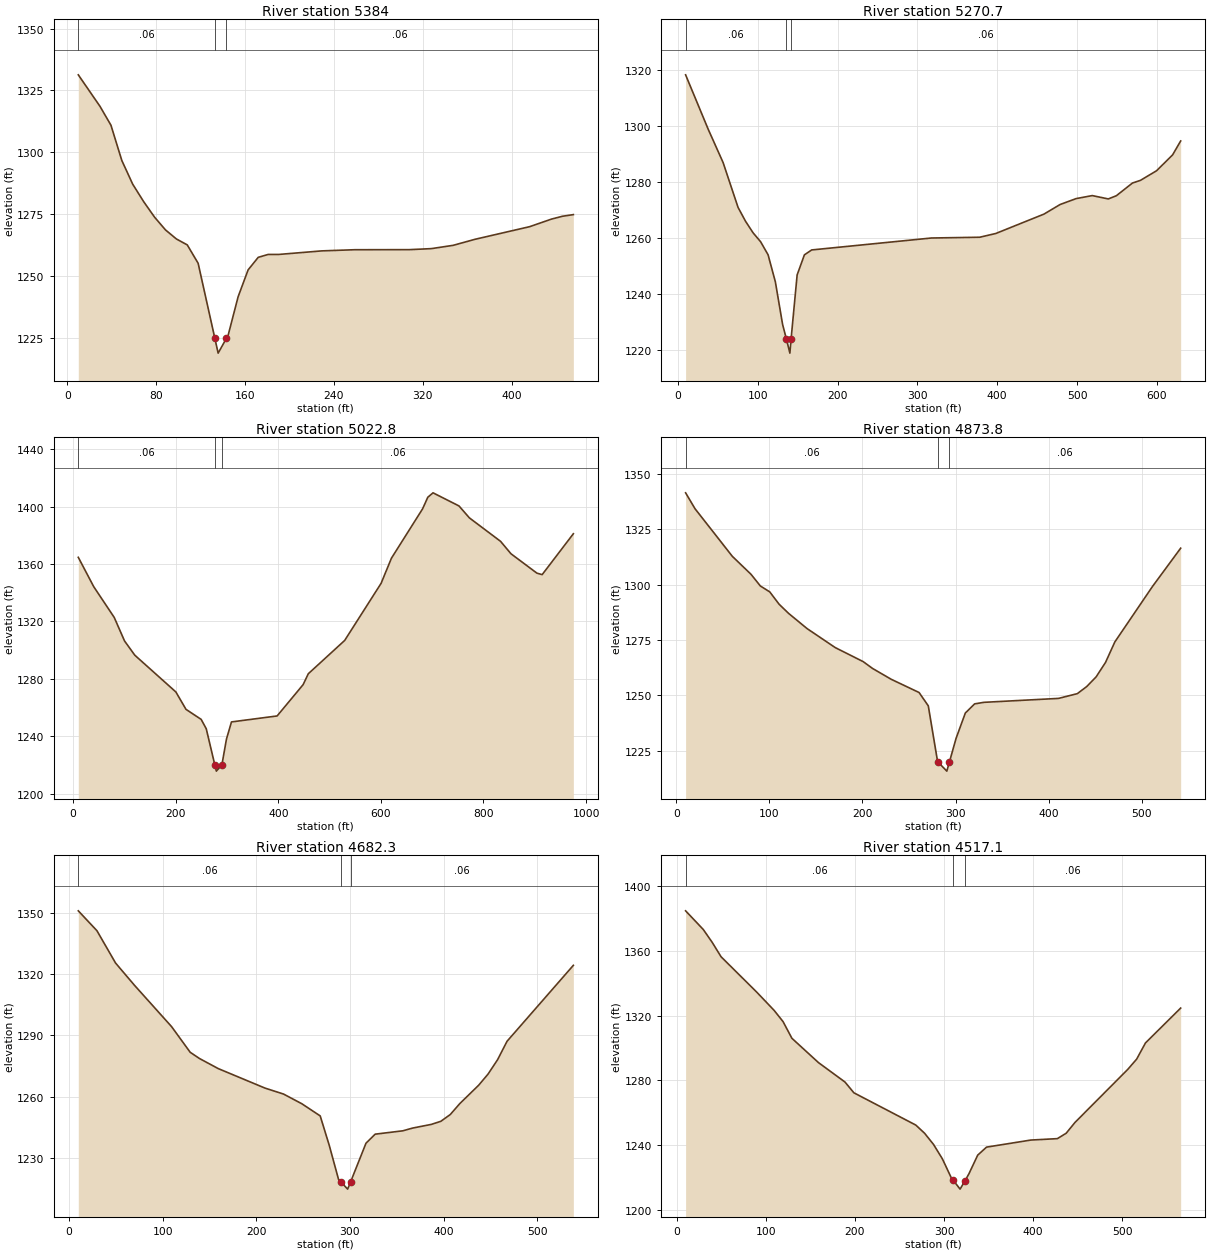
Type RM Length L Ch R = 1 ,5384    ,111.8,113.3,114.8
XS GIS Cut Line= 4
     1714310.654      205519.991     1714424.315      205550.556
     1714496.177      205556.083     1714757.345      205506.888
#Sta/Elev= 30
     9.8 1331.31    29.4 1318.54    39.2 1310.97      49 1296.72    58.8 1287.16
    68.7 1280.09    78.5 1273.84    88.3 1268.71    98.1 1265.06   107.9 1262.66
   117.7 1255.24   132.7 1225.04   135.7 1218.97   143.2 1224.96   144.7 1226.16
   153.7 1241.74   162.7 1252.58   171.8 1257.64   180.8 1258.81   189.8 1258.79
   229.1 1260.24   258.7 1260.71   307.9 1260.74   327.6 1261.15   347.3 1262.48
   366.9 1264.91   416.2 1270.02   435.8 1273.07   445.7 1274.22   455.5 1274.88
#Mann= 3 , 0 , 0
     9.8     .06       0   132.7    .045       0   143.2     .06       0
Bank Sta=132.7,143.2
XS Rating Curve= 0 ,0
Exp/Cntr=0.3,0.1

Type RM Length L Ch R = 1 ,5270.7  ,245.9,248,250.1
XS GIS Cut Line= 4
     1714308.272      205602.778     1714405.219      205660.358
     1714468.287      205669.906     1714885.529      205492.583
#Sta/Elev= 30
     9.4 1318.19    37.6 1298.87    56.4 1286.91    75.2 1270.88    84.6 1265.94
      94 1261.85   103.4 1258.68   112.8 1254.01   121.9 1244.38     131 1229.15
  135.78 1223.95   140.1 1218.96   141.6 1223.98   149.2 1246.86   158.3    1254
   167.4 1255.75   317.6 1260.01     378 1260.28   398.2 1261.62   458.6 1268.53
   478.8 1271.95   498.9 1274.06   519.1 1275.13   539.2 1273.94   549.3 1275.08
   569.5 1279.61   579.5 1280.56   599.7 1283.99   619.8 1289.65   629.9  1294.6
#Mann= 3 , 0 , 0
     9.4     .06       0  135.78    .045       0   141.6     .06       0
Bank Sta=135.78,141.6
XS Rating Curve= 0 ,0
Exp/Cntr=0.3,0.1

Type RM Length L Ch R = 1 ,5022.8  ,152.2,149,145.8
XS GIS Cut Line= 4
     1714169.765      205724.112     1714290.746      205883.797
     1714471.908      205931.034     1715054.941      206005.053
#Sta/Elev= 30
      10 1364.69    40.1 1344.24    80.1 1322.79   100.2  1306.4   120.2 1296.49
   200.3 1270.86     220 1258.75   249.6 1251.75   259.5 1245.24  276.24    1220
   279.2  1215.7  289.99    1220   298.9 1238.01   308.7 1249.99   397.7 1254.15
   448.4 1275.97   458.5 1283.56   529.4 1306.76   600.4 1346.54   620.6 1364.08
   681.4 1398.52   691.5 1406.54   701.7 1409.64   752.3  1400.5   772.6 1392.18
   833.4 1375.83   853.7 1367.17   904.3 1353.66   914.5 1352.64   975.3 1381.11
#Mann= 3 , 0 , 0
      10     .06       0  276.24    .045       0  289.99     .06       0
Bank Sta=276.24,289.99
XS Rating Curve= 0 ,0
Exp/Cntr=0.3,0.1

Type RM Length L Ch R = 1 ,4873.8  ,185.8,191.5,197.1
XS GIS Cut Line= 4
     1714074.118      205916.289     1714268.113      206041.483
     1714406.811      206055.219     1714535.765      206168.289
#Sta/Elev= 30
      10 1341.55    20.1 1334.37    60.2 1312.83    80.3 1304.69    90.3 1299.42
   100.4 1296.75   110.4 1291.19   120.5 1287.08   140.5 1280.15   170.7 1271.57
   200.8  1265.2   210.8 1262.13   230.9 1257.22   260.8 1251.24   270.7 1245.22
   280.7 1219.99   290.6 1215.69  293.43 1219.88   300.6 1230.59   310.5 1241.97
   320.5 1246.11   330.4  1246.8   410.6 1248.58   430.8 1250.73   440.9 1253.94
     451 1258.32   461.1 1264.86   471.1 1274.12   511.5 1299.18   541.8 1316.51
#Mann= 3 , 0 , 0
      10     .06       0   280.7    .045       0  293.43     .06       0
Bank Sta=280.7,293.43
XS Rating Curve= 0 ,0
Exp/Cntr=0.3,0.1

Type RM Length L Ch R = 1 ,4682.3  ,166.5,165.2,163.9
XS GIS Cut Line= 4
     1713981.784      206190.957      1714210.49      206205.847
     1714319.483      206249.325     1714482.674      206350.575
#Sta/Elev= 30
      10 1350.88    29.9 1341.17    49.8 1325.39    69.8 1314.62   109.6 1294.33
   129.5 1281.79   139.5 1278.73   159.4 1273.84   209.3 1264.32   229.2 1261.39
   248.7 1256.66   268.3 1250.73   278.1 1236.15   287.9 1219.71   290.1 1218.64
   297.6 1214.97  300.69 1218.42   317.2  1237.4     327 1241.81   356.6 1243.45
   366.8 1244.77     387 1246.59   397.1 1248.09   407.2  1251.4   417.3 1256.71
   437.5 1265.71   447.6  1271.2   457.7 1278.18   467.8 1287.17   538.6 1324.26
#Mann= 3 , 0 , 0
      10     .06       0   290.1    .045       0  300.69     .06       0
Bank Sta=290.1,300.69
XS Rating Curve= 0 ,0
Exp/Cntr=0.3,0.1

Type RM Length L Ch R = 1 ,4517.1  ,227.7,229,230.4
XS GIS Cut Line= 4
     1713919.529      206333.465     1714136.588      206359.936
     1714353.647      206430.877     1714472.235      206430.877
#Sta/Elev= 30
     9.9 1384.86    29.8 1373.27    39.8 1365.32    49.7 1356.45    89.5 1334.71
   109.3 1323.26   119.3 1316.33   129.2 1306.03     159    1291   188.8 1278.96
   198.8  1272.3   268.3 1252.34   278.2 1247.26   288.2 1240.36   298.1 1231.48
     308 1219.86   310.5 1218.07     318 1212.72   323.4 1217.74   327.9 1222.17
   337.8 1233.75   347.7  1238.7   397.4 1243.07   427.2 1243.95   437.1 1247.29
     447 1253.98   506.3 1286.83   516.2 1293.13   526.1 1303.14   565.6  1324.7
#Mann= 3 , 0 , 0
     9.9     .06       0   310.5    .045       0   323.4     .06       0
Bank Sta=310.5,323.4
XS Rating Curve= 0 ,0
Exp/Cntr=0.3,0.1

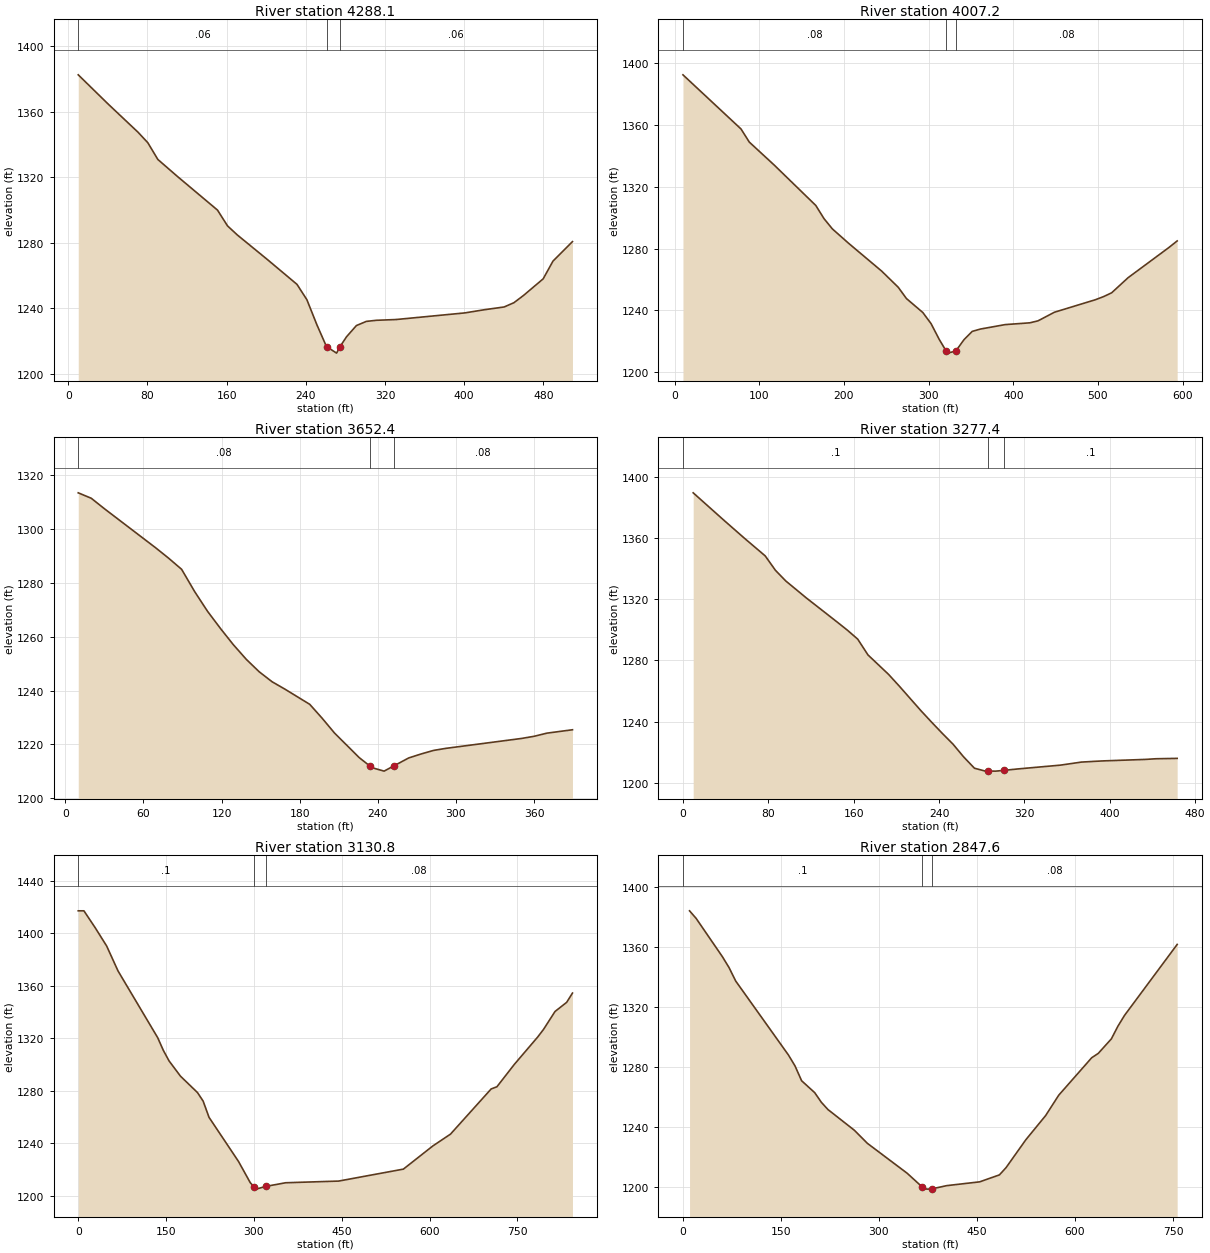
Type RM Length L Ch R = 1 ,4288.1  ,278.5,280.9,283.4
XS GIS Cut Line= 4
     1713898.353      206536.759     1714094.235      206582.288
        1714252.      206645.818     1714389.647      206658.524
#Sta/Elev= 30
    10.1 1382.38    40.2 1364.63    70.4 1347.44    80.4 1340.98    90.5 1330.79
   110.6 1320.27   150.8  1299.9   160.9 1290.29   170.9 1284.71   201.1 1269.81
   231.1 1254.63   241.1 1245.26   251.1 1230.14   261.1 1216.39   263.6 1215.64
   271.1 1212.71  274.11 1216.27   281.1 1222.64   291.1 1229.51   301.1 1232.05
   311.2 1232.72   331.2 1233.19   400.8 1237.24   420.5 1239.18   440.3 1240.84
   450.2 1243.43     460  1247.9   479.8    1258   489.7  1268.8   509.4  1280.7
#Mann= 3 , 0 , 0
    10.1     .06       0   261.1    .045       0  274.11     .06       0
Bank Sta=261.1,274.11
XS Rating Curve= 0 ,0
Exp/Cntr=0.3,0.1

Type RM Length L Ch R = 1 ,4007.2  ,360.1,354.7,349.4
XS GIS Cut Line= 4
     1713843.294      206729.465     1714020.118      206814.171
      1714224.47      206926.406     1714380.118      206979.347
#Sta/Elev= 30
     9.8 1392.58    78.4 1357.51    88.2 1349.01   117.6 1334.15   166.7    1308
   176.5  1299.4   186.3 1292.81   205.8 1283.34   244.6 1265.45   264.1 1255.02
   273.8 1247.71   293.2 1238.63   302.9 1231.45   312.6 1221.18  320.64  1213.8
   322.4 1212.36   332.1 1213.71   341.8 1221.07   351.5 1226.44   361.2 1227.95
   390.4 1230.83   419.5 1231.98   429.2 1233.26   448.6 1238.84   496.9 1246.92
   506.6 1248.94   516.2 1251.42   535.6 1261.19   583.9 1280.78   593.6 1285.02
#Mann= 3 , 0 , 0
     9.8     .08       0  320.64    .045       0   332.1     .08       0
Bank Sta=320.64,332.1
XS Rating Curve= 0 ,0
Exp/Cntr=0.3,0.1

Type RM Length L Ch R = 1 ,3652.4  ,365.5,375,384.5
XS GIS Cut Line= 4
     1713796.706       207067.23     1713922.706      207179.465
     1714070.463      207215.425     1714138.228      207226.719
#Sta/Elev= 30
     9.9 1313.42    19.9  1311.4    29.8 1307.59    69.5 1292.95    79.4 1289.11
    89.3 1285.01    99.3 1276.75   109.2 1269.42   119.1 1263.06     129 1257.03
     139 1251.56   148.9 1246.95   158.8 1243.25   168.7 1240.49   187.7 1234.87
   197.3 1229.67   206.8 1224.17   225.8 1215.04  234.08 1211.89   235.3 1211.38
   244.8 1210.06   252.3 1212.01   263.8 1214.97   273.3 1216.44   282.8 1217.75
   292.3 1218.52   350.3 1222.19   360.1    1223   369.9 1224.17   389.5 1225.42
#Mann= 3 , 0 , 0
     9.9     .08       0  234.08    .045       0   252.3     .08       0
Bank Sta=234.08,252.3
XS Rating Curve= 0 ,0
Exp/Cntr=0.3,0.1

Type RM Length L Ch R = 1 ,3277.4  ,152.2,146.6,141
XS GIS Cut Line= 4
     1713584.941      207386.994     1713770.235      207439.936
     1713895.404      207541.072     1714004.581      207550.484
#Sta/Elev= 30
     9.6 1389.51    38.5 1371.51    57.8 1359.72    77.1 1348.27    86.7 1338.84
    96.4 1331.87   115.6 1320.81   144.5 1305.05   154.2 1299.66   163.8 1293.86
   173.4 1283.54   192.7 1270.82   202.8 1263.11   222.9 1247.19   232.9 1239.68
     243  1232.3   253.1 1225.21   263.1 1216.84   273.2 1209.46   283.2 1207.61
   285.8  1207.6   293.3 1207.56   300.8 1208.06   313.4 1208.96   353.6 1211.46
   373.6 1213.48   393.5 1214.24   433.3 1215.21   443.3 1215.65   463.2 1215.89
#Mann= 3 , 0 , 0
       0      .1       0   285.8    .045       0   300.8      .1       0
Bank Sta=285.8,300.8
XS Rating Curve= 0 ,0
Exp/Cntr=0.3,0.1

Type RM Length L Ch R = 1 ,3130.8  ,280.1,283.2,286.3
XS GIS Cut Line= 4
      1713470.56      207507.045     1713671.485      207578.693
     1714060.388      207743.648     1714120.719       207943.04
#Sta/Elev= 30
       0 1417.23     9.7 1417.23    29.1 1404.24    48.5 1390.45    67.9 1371.46
   135.7 1320.57   145.4 1310.85   155.1  1302.9   174.5  1291.3   203.6 1278.79
   213.3 1272.27   223.4 1259.87   273.7 1226.29   293.8 1210.11  300.02 1207.05
   303.8  1205.2  319.83 1207.23   354.1 1210.05   444.7 1211.33   555.3 1220.44
   605.6 1238.09   635.8 1247.11   705.2 1281.51   715.1  1283.2   744.9 1300.29
   784.6 1321.02   794.5 1326.79   814.3 1340.54   834.2 1347.51   844.1 1354.57
#Mann= 3 , 0 , 0
       0      .1       0  300.02    .045       0  319.83     .08       0
Bank Sta=300.02,319.83
XS Rating Curve= 0 ,0
Exp/Cntr=0.3,0.1

Type RM Length L Ch R = 1 ,2847.6  ,414.7,430.8,447
XS GIS Cut Line= 4
     1713323.059      207647.641     1713557.412        207822.7
     1713788.941        207966.7     1713944.235       208078.23
#Sta/Elev= 30
    10.1 1384.05    20.2    1379    60.5  1353.4    70.6 1346.18    80.7 1337.28
   161.4 1287.98   171.5 1280.69   181.6 1270.79   201.7 1262.83   211.8 1256.44
   221.9  1251.6   262.3  1237.8   282.4 1229.02     343 1209.19   365.8 1200.14
   373.3 1198.54   380.8  1198.7   403.6 1200.86   454.1 1203.39   484.4 1208.04
   494.5 1212.86   524.8 1231.46   555.1 1247.57   575.2 1261.18   625.6 1286.13
   635.6    1289   655.7  1298.7   665.8 1307.21   675.9 1314.39   756.4 1361.64
#Mann= 3 , 0 , 0
       0      .1       0   365.8    .045       0   380.8     .08       0
Bank Sta=365.8,380.8
XS Rating Curve= 0 ,0
Exp/Cntr=0.3,0.1

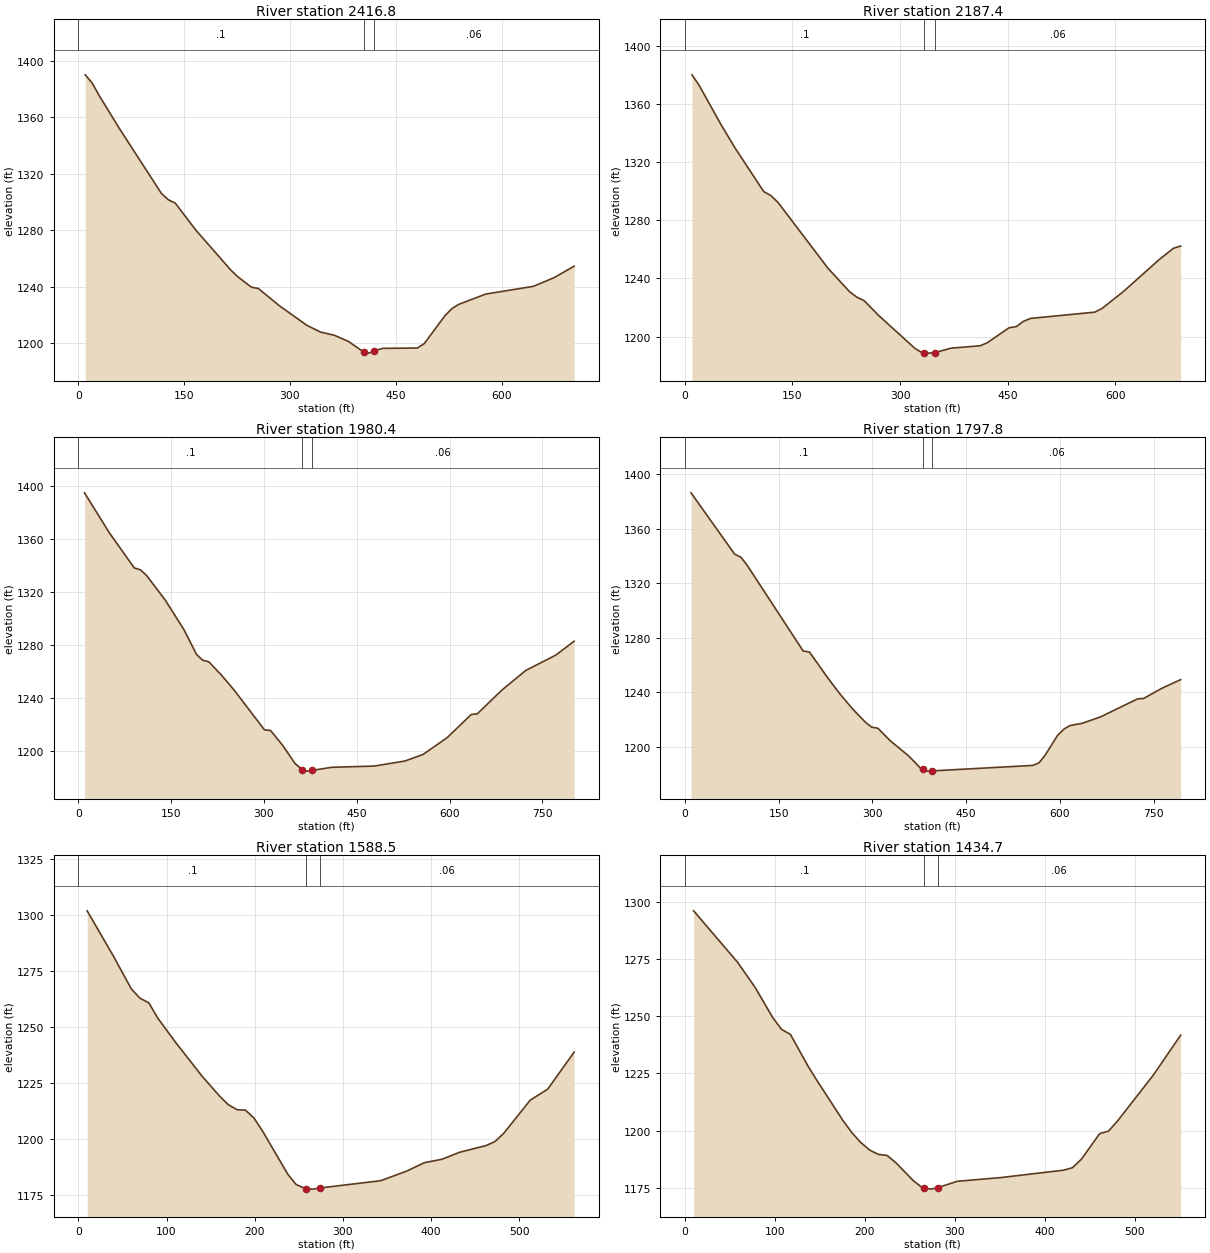
Type RM Length L Ch R = 1 ,2416.8  ,227.3,229.4,231.6
XS GIS Cut Line= 4
     1713152.235      207723.877     1713256.706      207977.994
     1713306.118      208208.112     1713397.882      208377.524
#Sta/Elev= 30
     9.8 1389.98    19.6 1384.19    29.4 1375.45    58.9 1351.46   117.8 1306.05
   127.6 1301.56   137.4 1299.19   166.8 1279.97   215.9 1251.96   225.7 1247.28
   245.3 1239.71   255.1  1238.8   284.6 1226.74   323.8 1212.79   343.4 1207.94
     363 1205.69   382.6 1201.41   404.5 1193.89     412 1193.07   419.5 1194.77
   431.7 1196.44   480.7 1196.68   490.5  1199.9   519.8 1219.64   529.4 1224.54
     539 1227.55   577.6 1234.87     645 1240.32   673.9 1246.37   702.8 1254.59
#Mann= 3 , 0 , 0
       0      .1       0   404.5    .045       0   419.5     .06       0
Bank Sta=404.5,419.5
XS Rating Curve= 0 ,0
Exp/Cntr=0.3,0.1

Type RM Length L Ch R = 1 ,2187.4  ,209.3,207,204.7
XS GIS Cut Line= 4
     1712948.968      207816.615     1713048.497      208034.733
     1713069.674      208235.909     1713175.556      208461.439
#Sta/Elev= 30
      10 1379.87      20 1372.66    49.9 1346.21    69.9 1329.77   109.9 1299.78
   119.9 1296.97   129.9 1292.28   199.8 1246.91   229.8 1230.88   239.8 1227.19
   249.9 1224.82   270.1 1214.68   320.7 1192.06   330.8 1188.96   333.4  1188.9
   340.9 1188.74   348.4 1189.05   371.2 1192.16   411.7 1193.78   421.8  1195.9
     452 1206.15     462 1206.93   471.9 1210.52   481.9 1212.57   571.6 1216.88
   581.6 1219.41   611.5 1231.06   661.3 1252.98   681.2 1260.73   691.2  1262.3
#Mann= 3 , 0 , 0
       0      .1       0   333.4    .045       0   348.4     .06       0
Bank Sta=333.4,348.4
XS Rating Curve= 0 ,0
Exp/Cntr=0.3,0.1

Type RM Length L Ch R = 1 ,1980.4  ,183.1,182.6,182.2
XS GIS Cut Line= 4
     1712899.529      207818.465     1712836.733       208082.38
     1712893.882       208342.23     1712954.588      208599.171
#Sta/Elev= 30
      10 1394.95    50.2 1364.69    90.4 1338.16   100.5 1336.71   110.5 1332.36
   140.7 1313.71   170.8 1291.45   190.9 1272.84     201  1268.4     211 1267.17
   231.1 1257.23   251.2 1246.19   300.8 1215.75   310.7 1215.28   330.4 1203.93
   350.1 1190.39   362.3 1185.41   369.8 1184.53   377.3 1185.02   409.2 1187.41
   478.2 1188.35   527.5 1192.13   556.9 1197.05     596  1209.8   635.1 1227.37
   644.9 1227.87     684 1245.55   723.1 1260.62     772 1272.33   801.4 1282.75
#Mann= 3 , 0 , 0
       0      .1       0   362.3    .045       0   377.3     .06       0
Bank Sta=362.3,377.3
XS Rating Curve= 0 ,0
Exp/Cntr=0.3,0.1

Type RM Length L Ch R = 1 ,1797.8  ,208.4,209.3,210.2
XS GIS Cut Line= 4
     1712745.647        207822.7     1712649.321      208084.498
     1712719.203      208373.556     1712758.353      208586.465
#Sta/Elev= 30
      10 1386.33    79.7 1341.33    89.7 1339.03    99.6 1333.25   189.3 1270.22
   199.3 1269.51   229.1  1250.2   249.1 1238.14     269 1227.35   288.9 1217.93
   298.8 1214.32   308.7 1213.57   328.5 1204.37   358.3 1193.06   378.1 1183.66
   380.5 1183.28     388 1182.06   395.5 1182.23   556.5 1186.25   566.4 1188.11
   576.3 1193.87     596 1208.26   605.9 1212.81   615.7 1215.48   635.4 1217.17
   664.9  1221.9   723.9 1235.06   733.8 1235.43   763.3 1242.97   792.8 1249.19
#Mann= 3 , 0 , 0
       0      .1       0   380.5    .045       0   395.5     .06       0
Bank Sta=380.5,395.5
XS Rating Curve= 0 ,0
Exp/Cntr=0.3,0.1

Type RM Length L Ch R = 1 ,1588.5  ,161.4,153.8,146.1
XS GIS Cut Line= 4
     1712395.203      208022.027     1712473.177      208184.112
     1712505.647      208353.524     1712583.294      208548.347
#Sta/Elev= 30
      10 1301.83      40 1281.48      60 1267.05    69.9 1262.84    79.9 1260.79
    89.9 1254.05   109.9 1243.34   139.9 1228.25   159.9 1219.26   169.9 1215.38
   179.9  1213.1   189.4 1212.93     199 1209.45   208.6 1203.73   237.4 1184.35
   246.9 1179.72   258.6 1177.72   266.1 1177.67   273.6 1178.17   342.8 1181.43
   372.3 1185.71   392.3 1189.47   412.3    1191   432.3 1194.13   462.2 1197.09
   472.2 1198.86   482.2 1202.54   512.2 1217.33   532.1 1222.27   562.1 1238.81
#Mann= 3 , 0 , 0
       0      .1       0   258.6    .045       0   273.6     .06       0
Bank Sta=258.6,273.6
XS Rating Curve= 0 ,0
Exp/Cntr=0.3,0.1

Type RM Length L Ch R = 1 ,1434.7  ,155,164.6,174.3
XS GIS Cut Line= 4
     1712256.497      208073.909      1712326.38      208277.203
     1712415.321      208416.968     1712451.321      208583.203
#Sta/Elev= 30
     9.8 1296.03    58.6 1273.58    78.2 1262.56    97.7  1249.4   107.5 1244.26
   117.3 1242.08   136.8 1228.27   146.6 1222.06   175.9 1204.33   185.7 1199.11
   195.4 1194.89   205.2 1191.59     215 1189.68   224.7 1189.22   234.5 1186.02
   253.9 1178.17   263.7 1175.18   265.9 1175.03   273.4 1174.51   280.9 1175.15
   302.7 1177.93   351.4 1179.57   420.7 1182.78   430.7 1183.88   440.7 1187.68
   460.7  1198.7   470.7 1199.88   480.7 1204.29   520.7 1224.47   550.7 1241.71
#Mann= 3 , 0 , 0
       0      .1       0   265.9    .045       0   280.9     .06       0
Bank Sta=265.9,280.9
XS Rating Curve= 0 ,0
Exp/Cntr=0.3,0.1

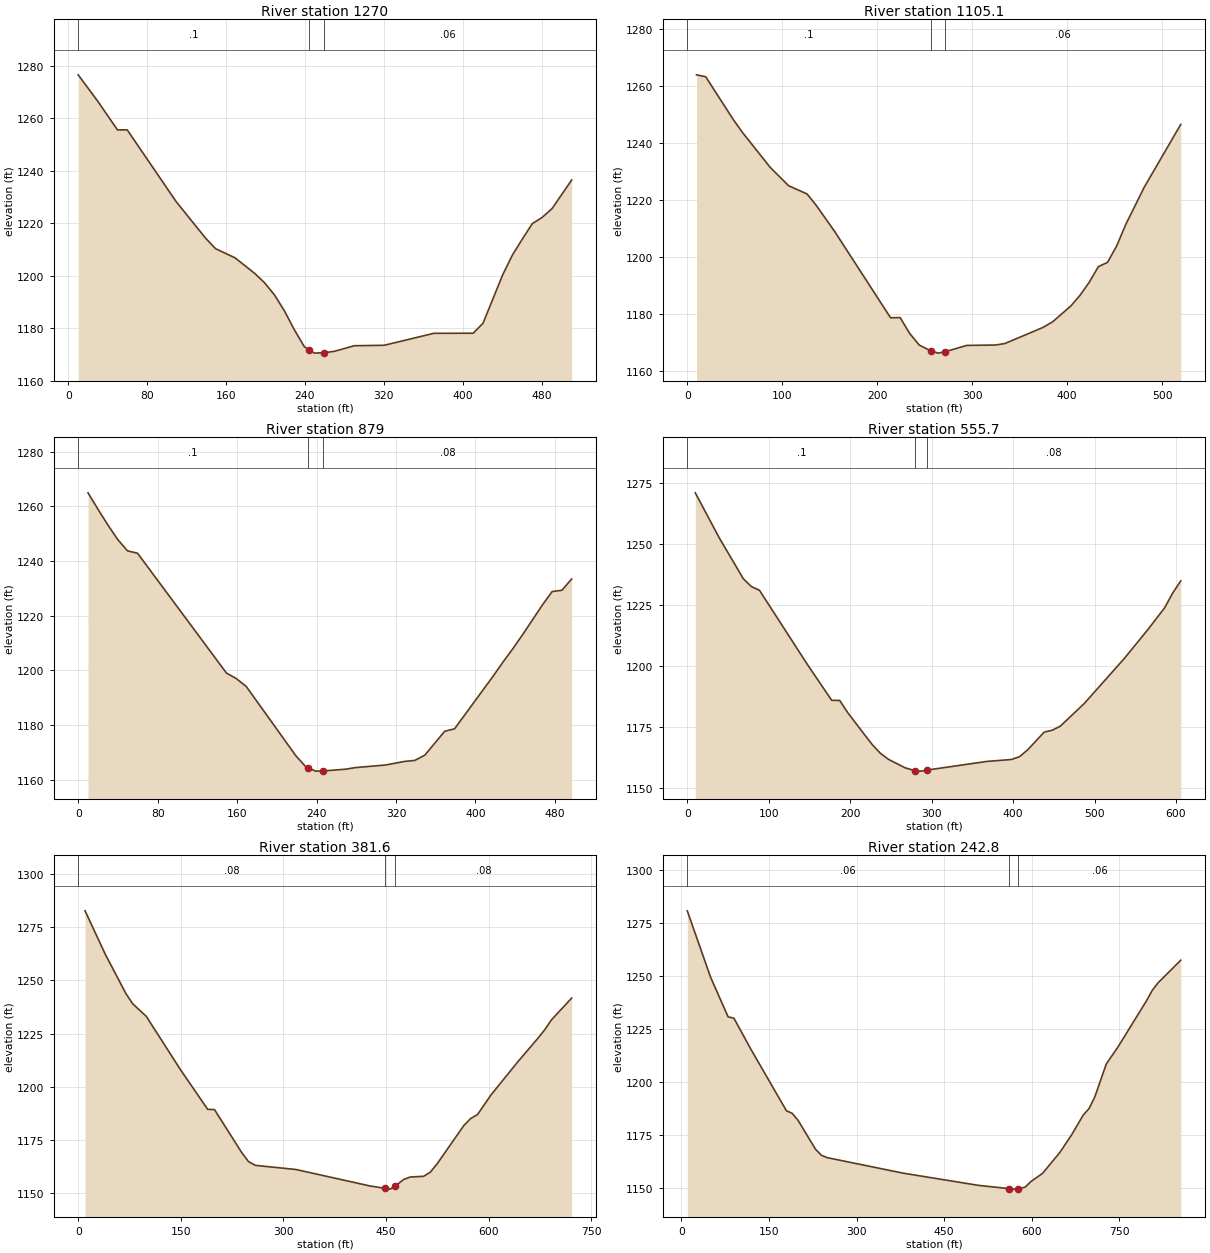
Type RM Length L Ch R = 1 ,1270    ,166.2,164.9,163.7
XS GIS Cut Line= 4
     1712144.262      208114.145     1712189.792      208307.909
     1712204.615       208468.85     1712245.909       208612.85
#Sta/Elev= 30
      10 1276.52    29.9 1266.42    49.8 1255.54    59.7 1255.55   109.5 1228.12
   139.3 1214.24   149.3 1210.28   169.2 1206.76   189.1 1200.82     199  1197.3
   209.1 1192.62   219.2 1186.55   229.3 1179.32   239.4 1172.88  244.21 1171.73
   249.5 1170.47   259.7 1170.65   269.8 1171.16     290 1173.29   320.3 1173.46
   370.7 1178.02   410.6 1178.05   420.6 1181.87   440.6 1200.36   450.5 1207.92
   460.5 1213.95   470.5 1219.78   480.5 1222.17   490.5  1225.5   510.5 1236.43
#Mann= 3 , 0 , 0
      10      .1       0  244.21    .045       0   259.7     .06       0
Bank Sta=244.21,259.7
XS Rating Curve= 0 ,0
Exp/Cntr=0.3,0.1

Type RM Length L Ch R = 1 ,1105.1  ,225,226.1,227.3
XS GIS Cut Line= 4
     1712061.674       208144.85     1712025.674      208335.439
     1712054.262      208523.909     1712115.529      208644.112
#Sta/Elev= 30
     9.7  1263.8    19.4 1263.12    48.5 1248.09    58.2 1243.54    87.3 1231.34
   106.7 1224.89   126.1 1222.01   135.8 1217.99   155.2 1208.83     214 1178.58
   224.1 1178.63   234.1  1173.1   244.1 1169.03   256.7  1166.9   264.2 1166.17
   271.7 1166.69   294.3 1168.88   324.4 1169.01   334.4 1169.54   374.6  1175.2
   384.6 1177.15   403.9 1182.74   413.5 1186.47   423.1    1191   432.8 1196.52
   442.4    1198     452 1203.73   461.7 1211.37     481 1224.33   519.5  1246.4
#Mann= 3 , 0 , 0
       0      .1       0   256.7    .045       0   271.7     .06       0
Bank Sta=256.7,271.7
XS Rating Curve= 0 ,0
Exp/Cntr=0.3,0.1

Type RM Length L Ch R = 1 ,879     ,332.9,323.3,313.7
XS GIS Cut Line= 4
     1711764.145      208188.262     1711804.941      208310.935
     1711829.412      208559.406     1711878.353        208666.7
#Sta/Elev= 30
     9.9 1264.92    19.9 1258.93    29.8 1253.22    39.8 1247.86    49.7  1243.7
    59.7 1242.87   149.3 1199.06   159.2 1197.05   169.2 1194.17   219.2 1168.83
   229.1 1164.84   231.6 1164.43   239.1 1163.23   246.6 1163.29   269.1 1163.93
   279.1 1164.52     309 1165.45     329 1166.79     339 1167.15     349 1169.06
     369 1177.78     379  1178.7   418.3 1198.17   428.1 1203.26   437.9 1208.08
   447.7  1213.2   467.4 1223.93   477.2 1228.84   487.1 1229.32   496.9 1233.45
#Mann= 3 , 0 , 0
       0      .1       0   231.6    .045       0   246.6     .08       0
Bank Sta=231.6,246.6
XS Rating Curve= 0 ,0
Exp/Cntr=0.3,0.1

Type RM Length L Ch R = 1 ,555.7   ,176,174.1,172.2
XS GIS Cut Line= 4
     1711441.203      208229.556     1711458.588      208425.759
     1711588.471      208629.053     1711720.235      208732.583
#Sta/Elev= 30
     9.8    1271    39.4 1252.46    68.9 1235.74    78.8 1232.56    88.6 1231.06
   147.7 1200.51   177.3 1185.95   187.1  1185.9     197  1180.9   217.1 1172.09
   227.1 1167.79   237.2 1164.19   247.2 1161.71   267.3  1158.3   279.9 1157.04
   287.4 1156.92   294.9 1157.38   367.9  1160.9     398 1161.69   408.1 1162.88
   418.1 1165.73   438.2 1172.91   448.1 1173.69   457.9 1175.33   487.5 1184.69
   536.8 1203.21   566.4 1215.34   586.1 1223.91   595.9 1229.92   605.8  1234.9
#Mann= 3 , 0 , 0
       0      .1       0   279.9    .045       0   294.9     .08       0
Bank Sta=279.9,294.9
XS Rating Curve= 0 ,0
Exp/Cntr=0.3,0.1

Type RM Length L Ch R = 1 ,381.6   ,141.8,138.8,135.8
XS GIS Cut Line= 4
     1711277.882      208207.406     1711300.471      208495.406
     1711471.765      208723.171     1711599.765      208796.582
#Sta/Elev= 30
      10 1282.69    39.8 1262.14    69.7 1243.83    79.7    1239    99.6 1233.07
   149.4  1208.1   189.3  1189.4   199.2 1189.31   239.1 1169.07     249 1164.84
     259 1163.09   318.4 1161.14   426.5 1153.41   448.4 1152.32   455.9 1151.92
   463.4 1153.33   475.6 1156.42   485.4 1157.61   505.1 1157.96   514.9 1159.95
   524.7  1163.8     564 1181.92   573.9 1185.12   583.7 1186.95   603.4 1196.15
   642.7 1211.77   672.2 1222.86   682.1 1226.85   691.9 1231.48   721.4  1241.7
#Mann= 3 , 0 , 0
       0     .08       0   448.4    .045       0   463.4     .08       0
Bank Sta=448.4,463.4
XS Rating Curve= 0 ,0
Exp/Cntr=0.3,0.1

Type RM Length L Ch R = 1 ,242.8   ,164.9,152.7,140.6
XS GIS Cut Line= 4
     1711225.177      208203.641     1711193.177      208612.112
     1711394.588      208819.171     1711547.059      208856.818
#Sta/Elev= 30
      10 1280.67      50 1249.37    79.9 1230.79    89.9 1230.11   119.9 1215.08
   179.9 1186.55   189.9 1185.32   199.9 1182.01   229.8 1168.42   239.8 1165.59
   249.8 1164.47   379.7 1157.18   509.3 1151.41   561.6 1149.88  569.21 1149.65
   576.6 1149.67     589 1150.61     599 1153.26   618.9  1157.1   648.8 1167.05
   668.7 1175.24   688.6 1184.55   698.6 1187.62   708.4 1193.11     728 1208.57
   747.7 1216.44   796.7 1238.21   806.6 1243.13   816.4 1246.68   855.6 1257.43
#Mann= 3 , 0 , 0
      10     .06       0   561.6    .045       0   576.6     .06       0
Bank Sta=561.6,576.6
XS Rating Curve= 0 ,0
Exp/Cntr=0.3,0.1

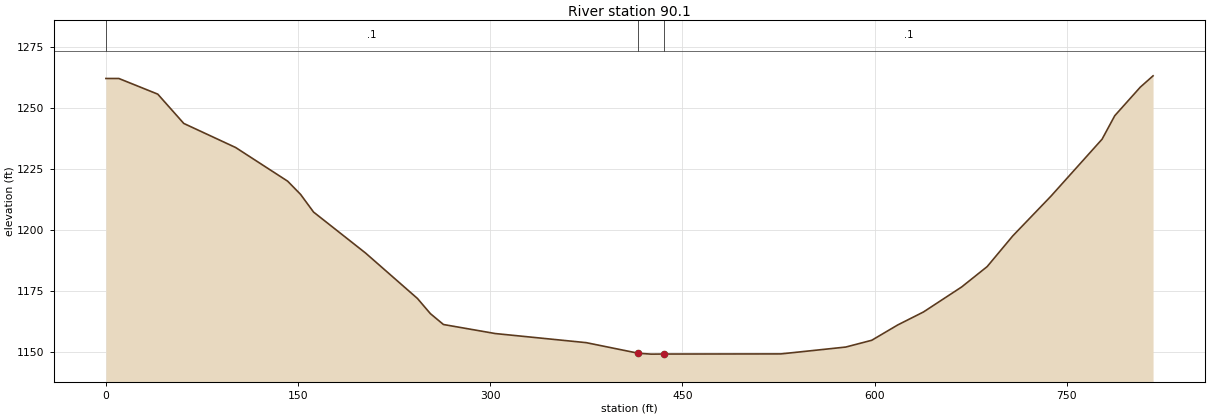
Type RM Length L Ch R = 1 ,90.1    ,75.5,90.1,104.6
XS GIS Cut Line= 4
     1710750.664       208528.15     1710905.637       208658.74
     1711281.207      208858.834     1711458.588      208924.582
#Sta/Elev= 30
       0 1262.11    10.1 1262.11    40.5 1255.68    60.8 1243.66   101.3 1233.78
   141.9 1219.96     152 1214.53   162.1  1207.3   202.7 1190.48   243.2 1171.84
   253.3 1165.62   263.5 1161.16     304 1157.45   374.9 1153.72   415.6 1149.37
   425.6 1149.01   435.6 1149.05   526.9  1149.1   577.5 1151.91   597.8 1154.69
   618.1 1160.98   638.2 1166.31     668 1176.57   687.9 1184.92   707.9 1197.52
   737.7 1213.82   777.6 1237.19   787.5 1246.83   807.4 1258.53   817.4  1263.2
#Mann= 3 , 0 , 0
       0      .1       0   415.6    .045       0   435.6      .1       0
Bank Sta=415.6,435.6
XS Rating Curve= 0 ,0
Exp/Cntr=0.3,0.1

Chan Stop Cuts=-1
Use User Specified Reach Order=0